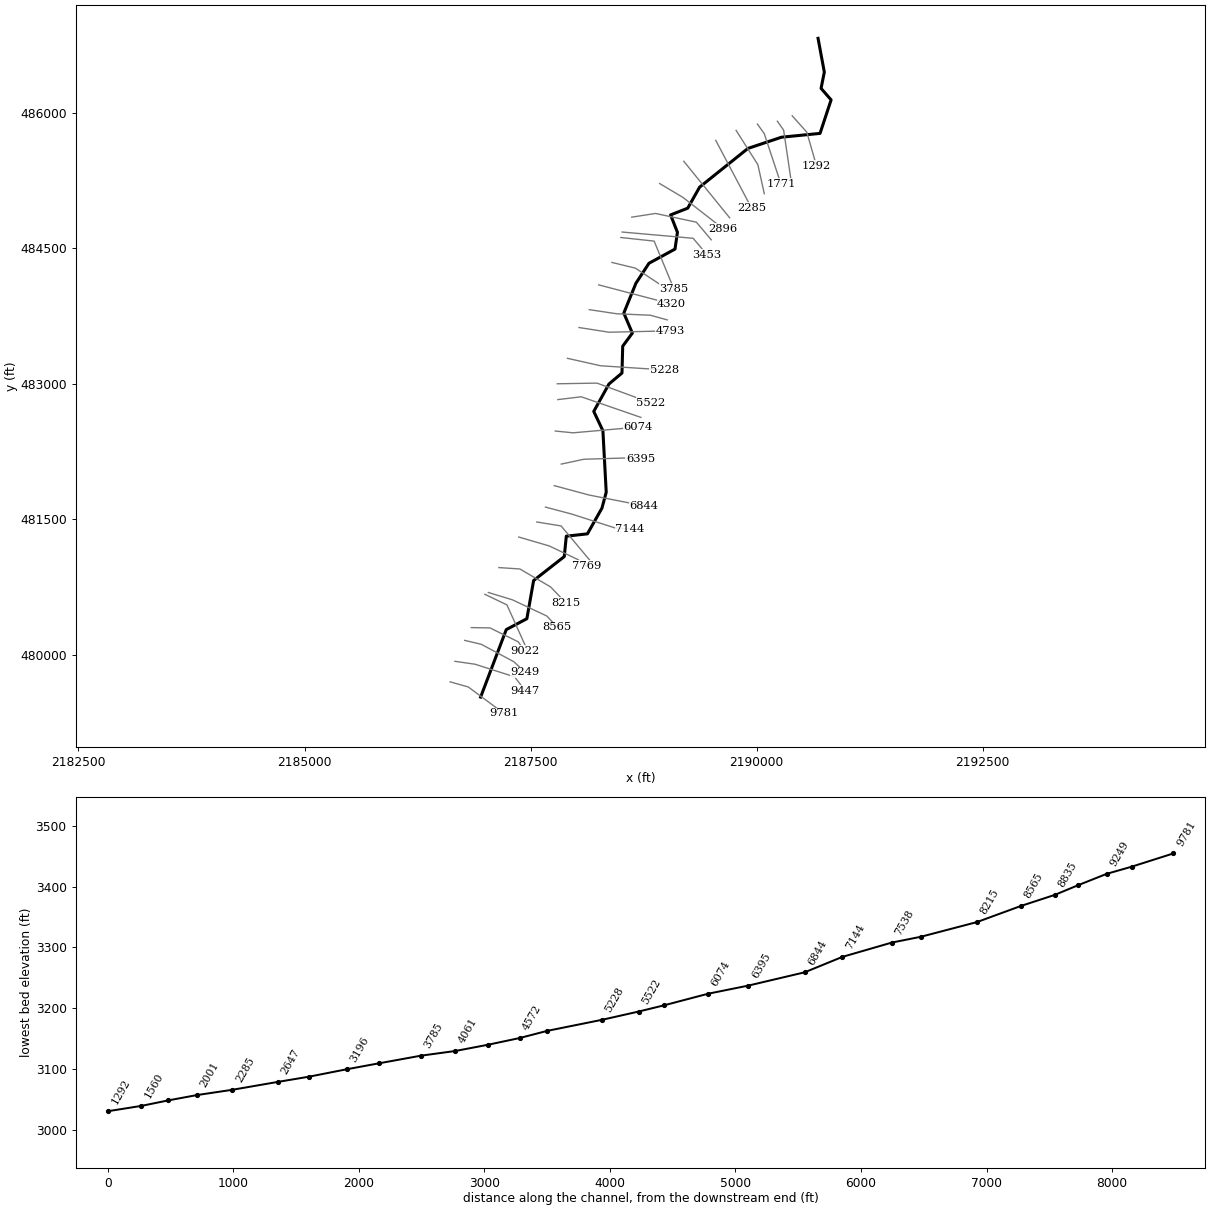
--- SUGARCK.prj (project) ---

Proj Title=SUGARCK
Current Plan=p01
Default Exp/Contr=0,0
English Units
Geom File=g01
Flow File=f01
Plan File=p01
BEGIN DESCRIPTION:
----------MODEL BY WOOD PLC 2021----------
Stream Name: Sugar Creek
Flood Zone: Enhanced Approximate
Pocahontas County, WV
HEC-RAS Version: RAS 6.1
Vertical Datum: NAVD88
Projection: NAD 1983 StatePlane West Virginia S FIPS 4702 (US Feet)
Terrain: 1-meter LIDAR (FEMA Region III 3DEP collected 2016-2018)
Land Use: 2019 NLCD
Hydrologic Method:
WV SIR2010-5033 regression equations
END DESCRIPTION:
DSS File=dss
DSS Export Rating Curves= 0
DSS Export Rating Curve Sorted= 0
DSS Export Volume Flow Curves= 0
DXF OffsetX= 0
DXF OffsetY= 0
DXF ScaleX= 0
DXF ScaleY= 0

--- SUGARCK.p01 (plan) ---

Plan Title=Floodplain
Program Version=6.10
Short Identifier=Floodplain
Geom File=g01
Flow File=f01
Subcritical Flow
K Sum by GR= 0
Std Step Tol= 0.01
Critical Tol= 0.01
Num of Std Step Trials= 20
Max Error Tol= 0.3
Flow Tol Ratio= 0.001
Split Flow NTrial= 30
Split Flow Tol= 0.02
Split Flow Ratio= 0.02
Log Output Level= 0
Friction Slope Method= 1
Unsteady Friction Slope Method= 2
Unsteady Bridges Friction Slope Method= 1
Parabolic Critical Depth
Global Vel Dist= 0 , 0 , 0
Global Log Level= 0
CheckData=True
Encroach Param=-1 ,0,0, 0
Computation Interval=0.1SEC
Output Interval=1SEC
Instantaneous Interval=Max Profile
Mapping Interval=1HOUR
Computation Time Step Use Courant=        0
Computation Time Step Use Time Series=    0
Computation Time Step Count To Double=0
Computation Time Step Max Doubling=0
Computation Time Step Max Halving=0
Computation Time Step Residence Courant=0
Run HTab= 0
Run UNet= 0
Run Sediment= 0
Run PostProcess= 0
Run WQNet= 0
Run RASMapper= 0
UNET Theta= 0
UNET Theta Warmup= 0
UNET ZTol= 0
UNET ZSATol= 0
UNET MxIter= 0
UNET Max Iter WO Improvement= 0
UNET MaxInSteps= 0
UNET DtIC= 0
UNET DtMin= 0
UNET MaxCRTS= 0
UNET WFStab= 0
UNET SFStab= 0
UNET WFX= 1
UNET SFX= 1
UNET Gravity=32.174
UNET 1D Methodology=Finite Difference
UNET DSS MLevel= 1
UNET Pardiso=0
UNET DZMax Abort= 0
UNET Use Existing IB Tables= 0
UNET Froude Reduction=False
UNET Froude Limit= 0
UNET Froude Power= 0
UNET D1 Cores= 0
UNET WindReference=Eulerian
UNET WindDragFormulation=Hsu (1988)
UNET D2 Coriolis=0
UNET D2 Cores= 0
UNET D2 Theta= 1
UNET D2 Theta Warmup= 1
UNET D2 Z Tol= 0.01
UNET D2 Volume Tol= 0.01
UNET D2 Max Iterations= 20
UNET D2 Equation= 0
UNET D2 RampUpFraction=0.1
UNET D2 TimeSlices= 1
UNET D2 Turbulence Formulation=Non-Conservative (original)
UNET D2 Eddy Viscosity=0.3
UNET D2 Transverse Eddy Viscosity=0.1
UNET D2 Smagorinsky Mixing=0
UNET D2 BCVolumeCheck=0
UNET D2 Cores=0
UNET D2 SolverType=PARDISO (Direct)
UNET D2 Minimum Iterations= 2147483647
UNET D2 Maximum Iterations= 2147483647
UNET D2 Restart Number= 10
UNET D2 Relaxation Coeff=1.3
UNET D2 SOR Precondition Iterations= 10
UNET D2 ILUT Maximum Fill= 8
UNET D2 ILUT Tolerance=1E-08
UNET D1D2 MaxIter= 0
UNET D1D2 ZTol=0.01
UNET D1D2 QTol=0.1
UNET D1D2 MinQTol=1
DSS File=dss
Write IC File= 0
Write IC File at Fixed DateTime=0
Write IC File at Sim End=0
Echo Input=False
Echo Parameters=False
Echo Output=False
Write Detailed= 0
HDF Write Warmup=0
HDF Write Time Slices=0
HDF Flush=0
HDF Compression= 1
HDF Chunk Size= 1
HDF Spatial Parts= 1
HDF Use Max Rows=0
HDF Fixed Rows= 1
Calibration Method= 0
Calibration Iterations= 20
Calibration Max Change=0.05
Calibration Tolerance=0.2
Calibration Maximum=1.5
Calibration Minimum=0.5
Calibration Optimization Method= 1
WQ AD Non Conservative
WQ ULTIMATE=-1
WQ Max Comp Step=1HOUR
WQ Output Interval=15MIN
WQ Output Selected Increments= 0
WQ Output face flow=0
WQ Output face velocity=0
WQ Output face area=0
WQ Output face dispersion=0
WQ Output cell volume=0
WQ Output cell surface area=0
WQ Output cell continuity=0
WQ Output cumulative cell continuity=0
WQ Output face conc=0
WQ Output face dconc_dx=0
WQ Output face courant=0
WQ Output face peclet=0
WQ Output face adv mass=0
WQ Output face disp mass=0
WQ Output cell mass=0
WQ Output cell source sink temp=0
WQ Output nsm pathways=0
WQ Output nsm derived pathways=0
WQ Create Restart=0
WQ Fixed Restart=0
WQ System Summary=0
WQ Write To DSS=0
Sorting and Armoring Iterations= 10
XS Update Threshold= 0.02
Bed Roughness Predictor= 0
Hydraulics Update Threshold= 0.02
Energy Slope Method= 1
Volume Change Method= 1
Sediment Retention Method= 0
Sediment TS Multiplier= 1
Warm Up Method= 0
XS Weighting Method= 0
Number of US Weighted Cross Sections= 1
Number of DS Weighted Cross Sections= 1
Upstream XS Weight=0
Main XS Weight=1
Downstream XS Weight=0
Number of DS XS's Weighted with US Boundary= 1
Upstream Boundary Weight= 1
Weight of XSs Associated with US Boundary= 0
Number of US XS's Weighted with DS Boundary= 1
Downstream Boundary Weight= 0.5
Weight of XSs Associated with DS Boundary= 0.5
Percentile Method= 0
Sediment Output Level= 3
Mass or Volume Output= 0
Output Increment Type= 1
Profile and TS Output Increment= 1
Transport Output Increment 1
XS Output Flag= 0
XS Output Increment= 10
Read HDF5 Sediment Hotstart= 0
Sediment Hotstart Type= 0
Write Gradation File= 0
Read Gradation Hotstart= 0
Write HDF5 File= 1
Write Binary Output= 1
Write DSS Sediment File= 0
DSS Sediment Output Type= 1
SV Curve= 0
Specific Gage Flag= 0
Subcell Erosion Methods= 0
Subcell Deposition Methods= 0
Advection Scheme= 1
Matrix Solver= 0
Implicit Weighting Factor= 1
Maximum Outer Loop Convergence Iterations= 5
Convergence Maximum Absolute= 0.001
Convergence RMSE= 0.0001
Grain Fractions Max Abs Error= 0.001
Max Subgrid Regions= 1
Max Subgrid Length Scale= 3.402823E+38
Initial Layer Thickness= 3.402823E+38
Min Layer Thickness= 3.402823E+38
Max Layer Thickness= 3.402823E+38
Number of Layers= 5

--- SUGARCK.f01 (steady flow) ---

Flow Title=USGS Regression Equation
Program Version=5.07
Number of Profiles= 6
Profile Names=01pct,10pct,04pct,02pct,0_2pct,01plus
River Rch & RM=SUGARCK,Main,9781
     577     305     406     489     806     854
River Rch & RM=SUGARCK,Main,7144
     759     405     536     644    1050    1120
River Rch & RM=SUGARCK,Main,4793
     847     454     600     719    1170    1250
Boundary for River Rch & Prof#=SUGARCK,Main            , 1
Up Type= 0
Dn Type= 3
Dn Slope=0.05486
Boundary for River Rch & Prof#=SUGARCK,Main            , 2
Up Type= 0
Dn Type= 3
Dn Slope=0.05486
Boundary for River Rch & Prof#=SUGARCK,Main            , 3
Up Type= 0
Dn Type= 3
Dn Slope=0.05486
Boundary for River Rch & Prof#=SUGARCK,Main            , 4
Up Type= 0
Dn Type= 3
Dn Slope=0.05486
Boundary for River Rch & Prof#=SUGARCK,Main            , 5
Up Type= 0
Dn Type= 3
Dn Slope=0.05486
Boundary for River Rch & Prof#=SUGARCK,Main            , 6
Up Type= 0
Dn Type= 3
Dn Slope=0.05486
DSS Import GetInterval= 0
DSS Import GetPeak= 0
DSS Import FillOption= 0

--- SUGARCK.g01 (geometry) ---

Geom Title=Geometry
Program Version=6.10

River Reach=SUGARCK         ,Main
Reach XY= 30
     2186948.253      479534.546     2187231.433      480280.593
     2187459.455      480401.295     2187534.254      480823.675
     2187873.177      481088.315     2187895.655      481313.964
     2188129.314      481339.981     2188289.931      481624.331
     2188337.244      481800.293     2188300.609      482480.335
     2188199.408      482694.1792188367.38693773482997.143139476
     2188511.595      483118.947     2188519.628      483415.709
     2188626.425      483560.358     2188531.711      483781.943
      2188665.74      484111.742     2188810.046      484332.656
     2189098.125      484489.764     2189124.959       484675.45
     2189049.166      484867.806     2189238.906      484942.256
2189370.36823156485174.934133364     2189904.216      485602.818
     2190275.429      485727.091     2190702.264       485769.36
      2190824.74      486139.884     2190713.816      486267.307
     2190749.629      486447.335     2190680.381      486820.832

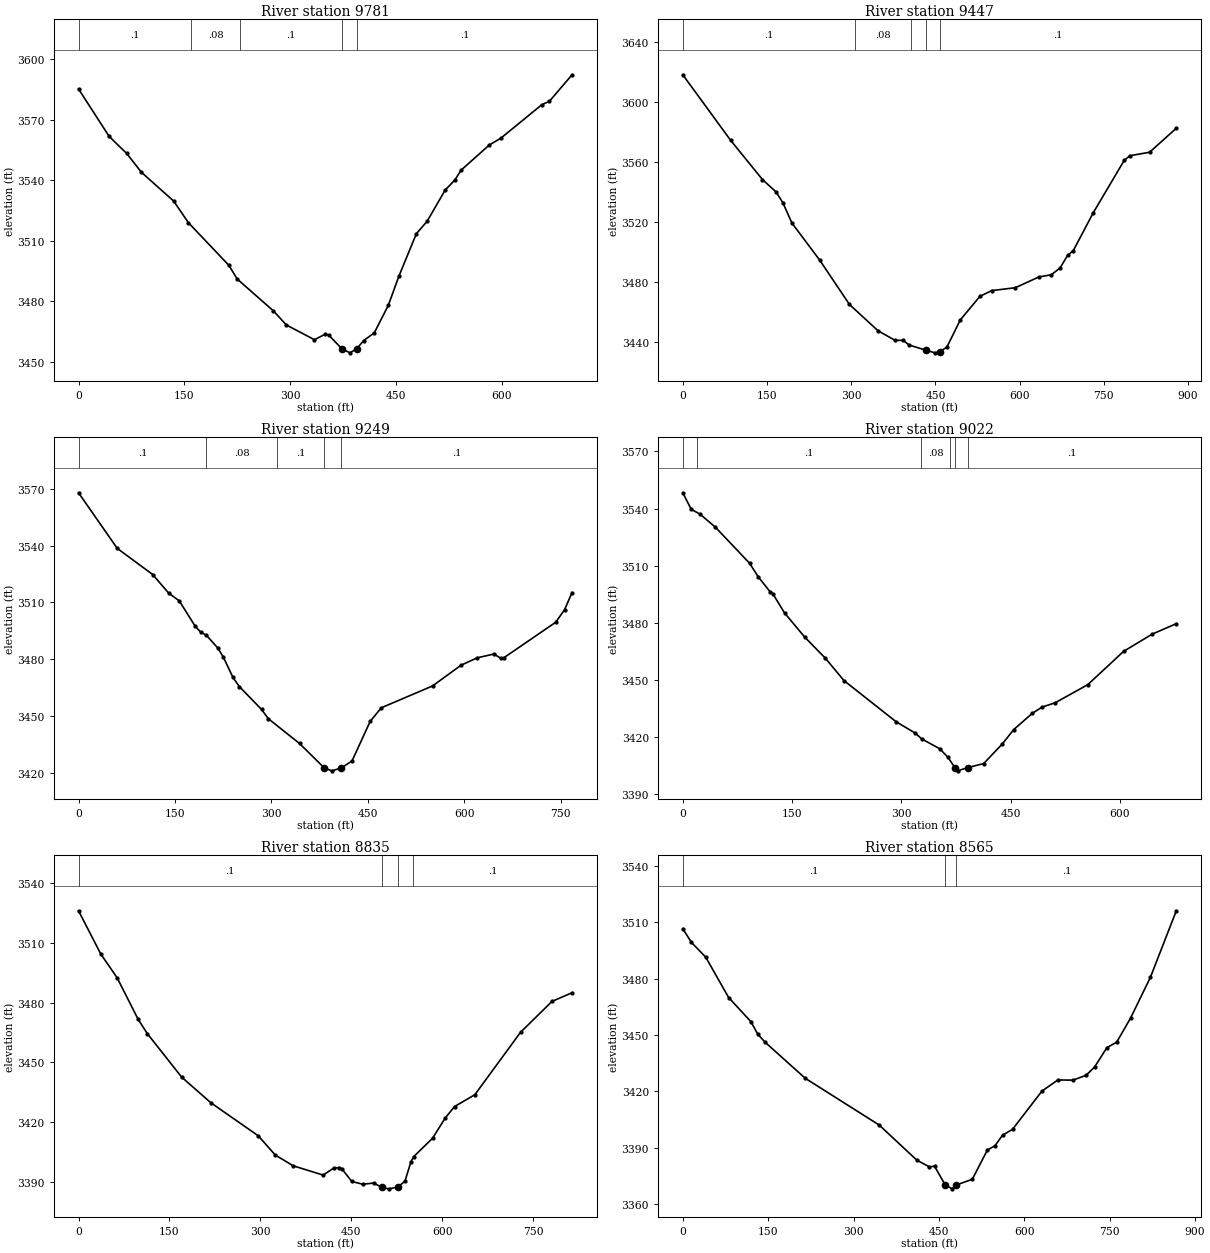
Type RM Length L Ch R = 1 ,9781    ,324.5,334.1,339.5
XS GIS Cut Line= 3
2186610.40711238479702.9549157112186811.56126118 479646.06967326
2187205.25155567479354.135131116
#Sta/Elev= 30
       0 3585.39    43.4 3561.83    68.3 3553.37    89.1 3544.05   134.9 3529.73
   155.6 3519.07     213 3497.91   224.7 3491.15   275.9 3475.36   294.5 3468.31
   334.3    3461   349.2  3463.7   354.2 3463.38   373.1 3456.53   384.5  3454.5
   394.1  3456.5     404 3460.59     419  3464.4   438.9 3478.09   453.8 3492.45
   478.7 3513.64   493.7 3519.67   519.5 3535.26   533.5 3540.36   541.8 3545.04
   581.8 3557.55   598.2 3560.93   656.2 3577.52   667.2  3579.3   699.2 3592.41
#Mann= 5 ,-1,0
       0      .1       0     160     .08       0  229.04      .1       0
   373.1    .045       0   394.1      .1       0
Bank Sta=373.1,394.1
XS Rating Curve= 0 ,0
Exp/Cntr=0.3,0.1

Type RM Length L Ch R = 1 ,9447    ,202,197.6,193.5
XS GIS Cut Line= 4
2186663.74591217479929.9553657552186887.38163995479897.587036733
2187324.35408174479757.8147068692187442.05709636479603.329500178
#Sta/Elev= 30
       0 3618.36    85.3 3574.54   141.9 3548.36   166.1 3540.08   178.3 3532.87
   194.4  3519.3   243.6 3494.67   296.9 3464.88   347.8 3447.31     378 3440.95
   392.4  3440.9   403.2 3437.81   432.9 3434.34   449.4 3432.58   457.8 3433.37
   470.4 3436.39   494.2 3454.55   529.1 3470.29   550.2 3474.17   592.2 3476.08
   634.3  3483.3   656.5 3484.75     672 3489.32   685.5 3497.76   695.6 3500.91
   730.7 3525.93   786.1 3561.11   796.2 3564.28   831.4  3566.6     879 3582.64
#Mann= 5 ,-1,0
       0      .1       0  305.97     .08       0  405.97      .1       0
   432.9    .045       0   457.8      .1       0
Bank Sta=432.9,457.8
XS Rating Curve= 0 ,0
Exp/Cntr(USF)=0,0
Exp/Cntr=0.3,0.1

Type RM Length L Ch R = 1 ,9249    ,223,227.4,226
XS GIS Cut Line= 4
2186771.94298506480161.4114956372186955.67284524480118.064533217
2187315.04705154479925.8235432972187439.98584255479809.194969154
#Sta/Elev= 30
       0 3567.98    60.2 3538.57   115.3 3524.75     140 3514.98   156.7 3510.78
   181.1 3497.54   189.8  3494.3   198.7 3492.67   216.6 3485.85   225.3 3480.97
     240 3470.39     250 3465.51   284.6 3453.38   295.1  3448.5   343.6  3435.4
   381.9 3422.55   393.7 3420.94   408.5 3422.45   425.2 3426.18   453.5 3447.13
   470.7 3454.27   550.4 3465.83   594.7 3476.79   619.8  3480.7   645.7  3482.7
     657 3480.36   661.8 3480.87   741.9 3499.52   755.6 3506.12   767.3 3515.24
#Mann= 5 ,-1,0
       0      .1       0  198.77     .08       0  308.77      .1       0
   381.9    .045       0   408.5      .1       0
Bank Sta=381.9,408.5
XS Rating Curve= 0 ,0
Exp/Cntr=0.3,0.1

Type RM Length L Ch R = 1 ,9022    ,198.8,186.4,170.4
XS GIS Cut Line= 4
 2186844.5576642480303.0142925282187051.63208515480299.563052179
 2187364.4084112480145.2408399732187434.29602827480046.000423737
#Sta/Elev= 30
       0 3548.31    11.6 3539.61    23.6 3537.12    44.7 3530.25    91.6 3511.33
   103.6 3504.17   119.6 3496.42   123.6 3495.28   139.6 3485.24   167.6 3472.41
   195.6 3461.47   221.2 3449.69   292.9 3428.03   319.2 3422.08   328.1 3419.02
   352.7 3413.87   363.8 3409.45   373.6 3403.89   377.2 3402.29   390.93403.977
   412.9  3406.1   438.5  3416.4   454.2 3423.97   479.8 3432.52     493 3435.76
     511 3438.02   555.8 3447.54   604.9 3465.01     644 3474.04   677.3 3479.58
#Mann= 6 ,-1,0
       0     .06       0      20      .1       0   327.1     .08       0
   367.1      .1       0   373.6    .045       0   390.9      .1       0
Bank Sta=373.6,390.9
XS Rating Curve= 0 ,0
Exp/Cntr(USF)=0,0
Exp/Cntr=0.3,0.1

Type RM Length L Ch R = 1 ,8835    ,251.9,270.3,284.4
XS GIS Cut Line= 3
2186994.94455791 480671.274178082187239.11128517480553.966219196
2187462.30316063480058.944946457
#Sta/Elev= 30
       0 3526.22    36.9 3504.35    63.5  3492.6    98.4 3471.55   113.4 3464.44
     170 3442.56   218.3 3429.62   296.5 3412.99   324.4 3403.35   353.9 3397.93
   403.4 3393.25   420.9 3396.78   429.7 3396.99   434.1 3396.45   450.7 3390.03
   468.9 3388.65   486.7 3389.24   499.9 3387.14   511.2 3386.33   526.5 3387.17
   538.4 3390.24   548.2 3399.96   552.6 3402.49   583.8 3411.77   604.9 3422.04
   620.1 3427.73   653.5 3433.66   728.9 3465.07   780.7  3480.6   813.9 3485.01
#Mann= 4 ,-1,0
       0      .1       0   499.9    .045       0   526.5     .08       0
  550.88      .1       0
Bank Sta=499.9,526.5
XS Rating Curve= 0 ,0
Exp/Cntr=0.3,0.1

Type RM Length L Ch R = 1 ,8565    ,348.3,349.8,340.8
XS GIS Cut Line= 4
2187033.67511765480691.2840264582187300.64581485480609.748473212
2187681.30036915480430.3702560722187794.67361461480307.678661665
#Sta/Elev= 30
       0 3506.57    15.2 3499.26    40.3 3491.41    80.6  3469.9   119.7 3457.07
   131.8 3450.35   144.8 3446.08   215.1 3426.95     345 3402.06   411.3 3383.32
   433.4 3379.77   442.2 3380.17   460.9 3370.24   473.2 3368.09   480.6 3370.13
   508.6 3373.18   535.1 3388.76   548.4 3391.02   561.7 3396.63   579.3 3399.77
   630.9 3420.11   658.9 3426.04   685.4 3425.95   708.5 3428.53   723.4 3432.93
   745.1 3443.25   762.3 3446.17   786.7 3459.02   821.4 3480.63     867  3516.1
#Mann= 3 ,-1,0
       0      .1       0   460.9    .045       0   480.6      .1       0
Bank Sta=460.9,480.6
XS Rating Curve= 0 ,0
Exp/Cntr(USF)=0,0
Exp/Cntr=0.3,0.1

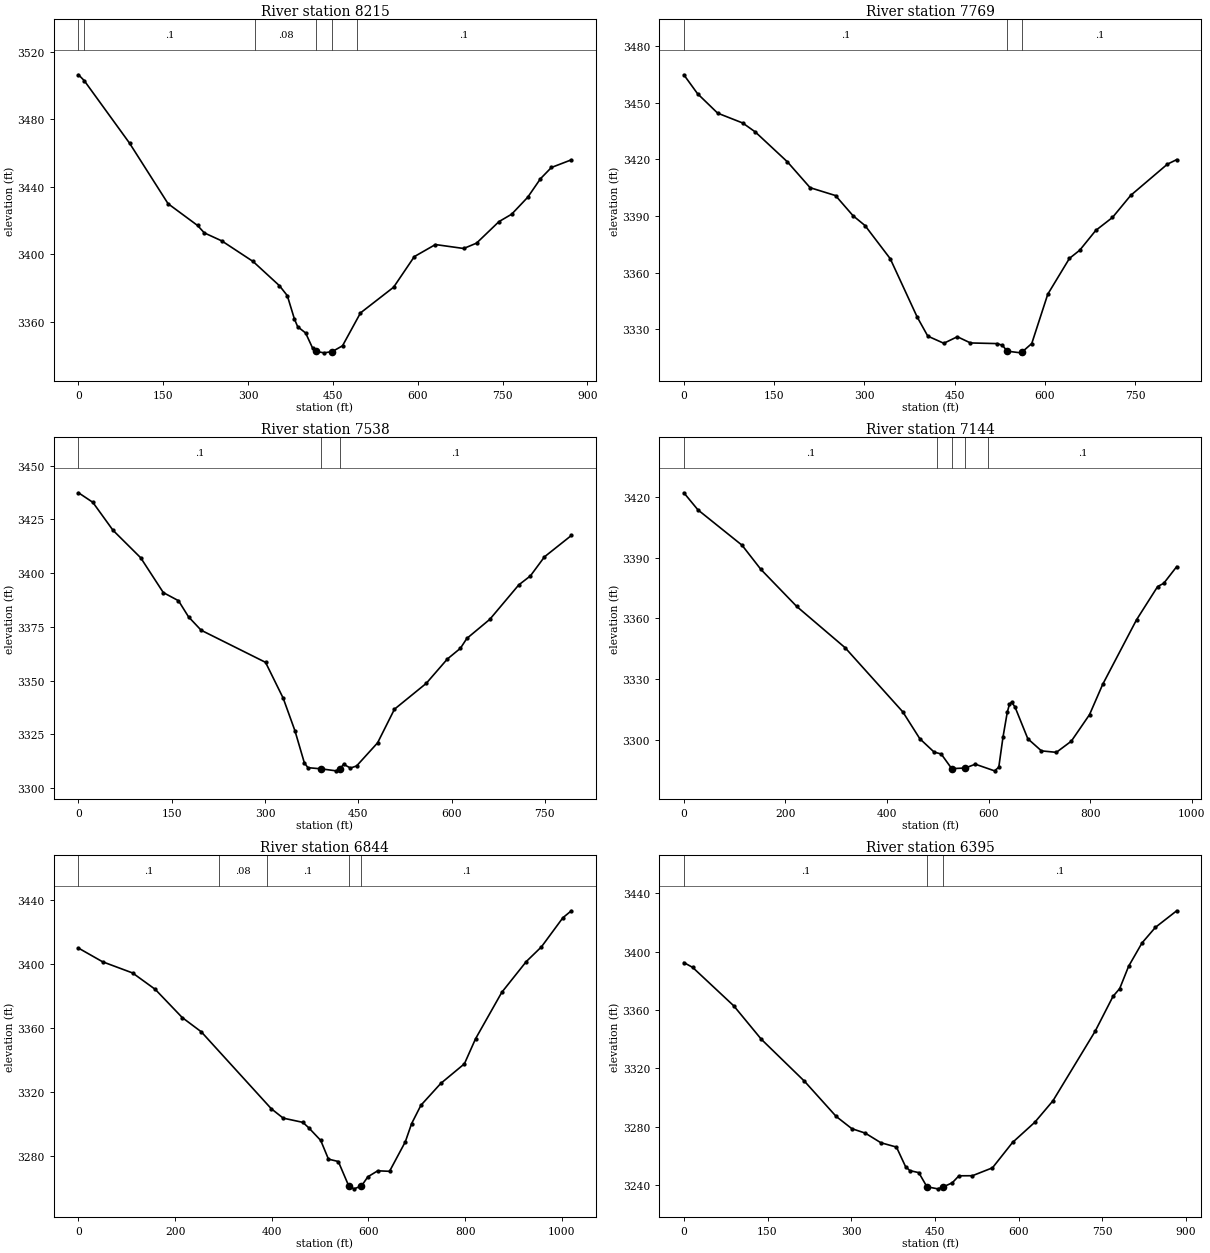
Type RM Length L Ch R = 1 ,8215    ,444,446.6,443.7
XS GIS Cut Line= 4
2187150.16759191480966.8054727872187382.16447508480951.335873863
2187721.68344051480753.1103587612187891.89720846480575.735941843
#Sta/Elev= 30
       0 3506.43      10 3503.03    90.2 3465.94   158.4 3430.02   210.5 3417.13
   222.5 3412.73   253.4 3407.98   308.7 3395.79   355.3 3381.44   369.2 3375.56
   381.8 3361.69   387.6 3357.12   401.6 3353.42   413.9 3344.49   420.1 3342.46
   434.4 3341.65     449 3342.43   466.9 3345.85   498.6  3365.3   557.2 3380.54
   593.8 3398.67   631.1 3405.82   681.1 3403.49   703.8 3406.65   743.4 3419.39
     766 3423.83   794.3 3433.84   816.9 3444.84   836.2 3451.49   871.5 3456.03
#Mann= 6 ,-1,0
       0     .06       0      10      .1       0  312.51     .08       0
   420.1    .045       0     449     .08       0  492.51      .1       0
Bank Sta=420.1,449
XS Rating Curve= 0 ,0
Exp/Cntr=0.3,0.1

Type RM Length L Ch R = 1 ,7769    ,235.9,230.9,209.2
XS GIS Cut Line= 4
2187370.26146549481304.5430762952187706.04175888481206.441299922
2188024.24004818481055.3678199342188116.29232283480983.611109454
#Sta/Elev= 30
       0 3464.82    22.8 3454.79    56.2 3444.49    97.8 3439.28   118.7 3434.54
     172 3418.72   209.8 3405.01     252 3400.84   281.2 3390.13     301 3384.96
   342.9 3367.39   387.6 3336.53   405.3 3326.38   431.9  3322.6   454.4 3326.06
   476.2 3322.77   520.4 3322.43   529.3 3321.52   537.1 3318.42   559.5 3317.53
   562.4  3318.1     578 3322.46   604.6 3348.59   640.6 3367.56   657.7 3371.89
   684.3 3382.36   712.1 3389.24   742.5 3400.97   803.3 3417.46   818.8 3419.87
#Mann= 3 ,-1,0
       0      .1       0   537.1    .045       0   562.4      .1       0
Bank Sta=537.1,562.4
XS Rating Curve= 0 ,0
Exp/Cntr=0.3,0.1

Type RM Length L Ch R = 1 ,7538    ,383.6,393.3,403.9
XS GIS Cut Line= 3
2187569.48018184  481470.91922132187838.15924301481427.433592902
2188172.06674678481028.297646539
#Sta/Elev= 30
       0 3437.42      23 3432.99    55.4    3420     100 3407.18   136.4 3390.97
   160.8 3387.19     177 3379.67   197.2 3373.46   300.8 3358.51   329.2 3341.82
   348.1 3326.65   363.2 3311.75   368.9  3309.5   389.8 3308.96   414.3 3308.02
     420 3308.85   426.4 3311.06   437.4 3309.32   447.2 3310.29     481 3321.06
   508.1  3336.7   559.2 3348.72   593.2 3360.06   614.1 3365.03   624.5 3369.63
   661.4 3378.51     708 3394.54   726.7 3398.73   749.4 3407.62   792.6 3417.55
#Mann= 3 ,-1,0
       0      .1       0   389.8    .045       0     420      .1       0
Bank Sta=389.8,420
XS Rating Curve= 0 ,0
Exp/Cntr(USF)=0,0
Exp/Cntr=0.3,0.1

Type RM Length L Ch R = 1 ,7144    ,295.9,300.8,299.3
XS GIS Cut Line= 4
 2187665.3144053481635.9491148822187954.20878359481559.095852972
2188430.32684139481406.662210408 2188601.5738694481393.853893545
#Sta/Elev= 30
       0 3422.13    27.8 3413.67   114.7 3396.16   151.7 3384.23   222.3 3365.89
   317.6 3345.47   431.2 3313.73   464.8 3300.41   492.9 3293.83   506.8 3292.88
   527.6 3285.63   554.5 3285.96     574 3287.84   611.8 3284.55   620.2 3286.31
   628.6 3301.37     637  3313.6   641.2 3317.45   645.4 3318.51     652 3316.24
   677.4 3300.43   704.2 3294.43   733.6  3293.7     763 3299.21   798.9 3312.35
   824.8 3327.31   891.5 3359.29   933.1 3375.75   945.1 3377.34   970.6 3385.59
#Mann= 5 ,-1,0
       0      .1       0  498.94     .08       0   527.6    .045       0
   554.5     .08       0  598.94      .1       0
Bank Sta=527.6,554.5
XS Rating Curve= 0 ,0
Exp/Cntr=0.3,0.1

Type RM Length L Ch R = 1 ,6844    ,444,449.1,453.5
XS GIS Cut Line= 3
2187762.95887132481873.1702589552188147.62253092481769.216835501
 2188757.3518355481649.503447869
#Sta/Elev= 30
       0 3409.94    49.9 3401.37   111.9 3394.38   158.7 3384.13   214.6 3366.46
     254 3357.54     399 3309.32   423.5 3303.47   464.2 3300.81   476.5 3297.39
   501.2 3289.49   517.2 3277.78   537.6  3276.3   559.1 3261.06   570.2 3259.18
   585.5 3260.99   598.8 3266.74   619.1 3270.47   643.6 3270.16   676.2 3288.62
   689.3 3300.05   708.5 3311.51   749.6  3325.2   798.5 3337.48   821.5 3353.14
   875.9 3382.28   926.6 3401.55   957.8  3410.7  1002.3 3428.97  1019.8 3433.32
#Mann= 5 ,-1,0
       0      .1       0     290     .08       0     390      .1       0
   559.1    .045       0   585.5      .1       0
Bank Sta=559.1,585.5
XS Rating Curve= 0 ,0
Exp/Cntr=0.3,0.1

Type RM Length L Ch R = 1 ,6395    ,318.4,320.2,320.3
XS GIS Cut Line= 4
2187840.69826899482111.6791842942188089.46454743482165.019172552
2188524.70430255482178.440662798 2188718.3528655482173.128010782
#Sta/Elev= 30
       0 3392.51    15.8 3389.19    89.5 3362.84   138.9 3339.91   216.3 3311.11
   273.1 3286.98   301.2 3278.59   325.2 3275.55   353.2 3268.95   381.2 3265.97
   397.4 3252.64   405.2 3249.83   421.2 3248.44   435.8 3238.75   455.2 3237.33
   465.2 3238.71   481.2 3241.46   493.2 3246.27   517.3 3246.32   553.3 3251.75
   589.3 3269.14   629.3 3283.03   661.7 3297.68   737.4  3345.4   769.4 3369.31
   781.4 3374.67   797.4 3389.97   821.4 3405.95   845.4 3416.64   883.6 3428.02
#Mann= 3 ,-1,0
       0      .1       0   435.8    .045       0   465.2      .1       0
Bank Sta=435.8,465.2
XS Rating Curve= 0 ,0
Exp/Cntr=0.3,0.1

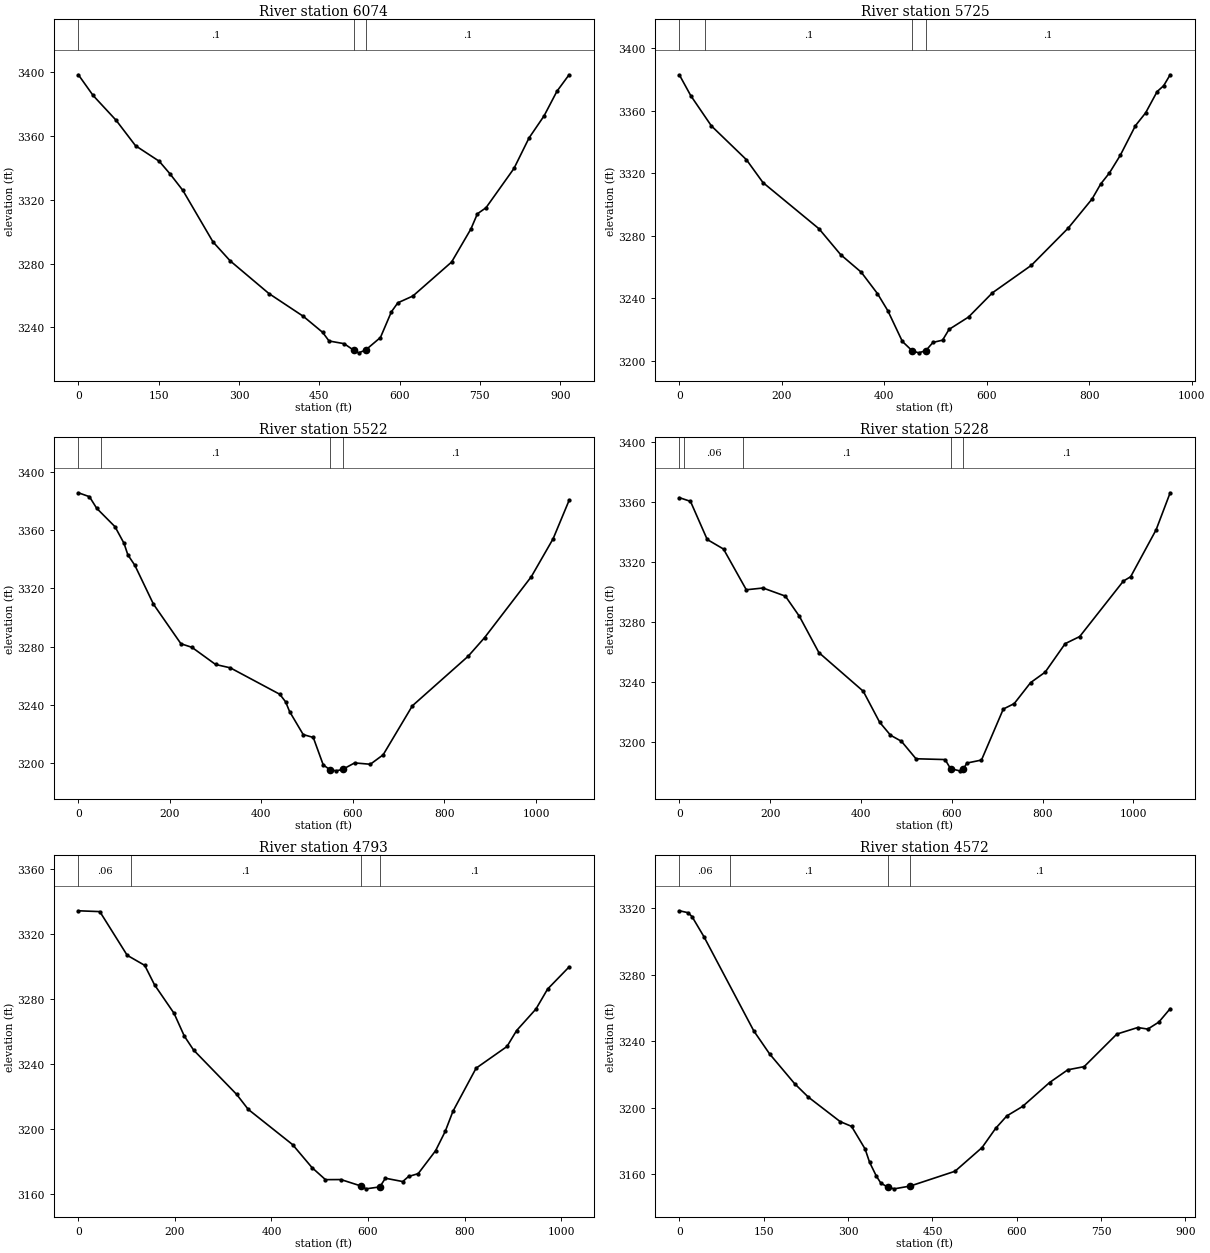
Type RM Length L Ch R = 1 ,6074    ,354.6,349.6,334.1
XS GIS Cut Line= 3
2187773.95095062482477.0640883582187971.03403075482457.495555579
2188686.68322952 482520.39441094
#Sta/Elev= 30
       0 3398.43    27.5 3385.44    70.6 3369.83   106.7 3353.93     151 3344.18
   171.1 3336.28   195.2 3325.86   251.4 3293.59   283.5 3281.68   355.8  3261.2
   420.3 3246.84   456.2 3236.83   468.2 3231.41   496.3 3229.72   514.2 3225.64
   523.6 3223.97   536.5 3225.72   564.2 3233.59   584.7 3249.74   596.7 3255.36
   624.8 3259.62   697.1 3280.93   733.2  3301.7   745.3  3311.2   761.4 3315.01
   813.6 3339.65   841.7 3358.77   869.8 3372.63   893.9  3388.1   916.5 3398.42
#Mann= 3 ,-1,0
       0      .1       0   514.2    .045       0   536.5      .1       0
Bank Sta=514.2,536.5
XS Rating Curve= 0 ,0
Exp/Cntr(USF)=0,0
Exp/Cntr=0.3,0.1

Type RM Length L Ch R = 1 ,5725    ,201.8,202.8,200.8
XS GIS Cut Line= 3
2187802.30335345482824.8667671812188061.10190113482855.954900855
2188720.18847659 482628.28171488
#Sta/Elev= 30
       0 3382.77      22 3369.62    62.3 3350.24   130.8 3328.57     163 3313.98
   272.4 3284.41   314.7 3267.84   354.9  3256.6   386.6 3242.88   406.8 3231.94
   435.1 3212.32   454.3 3206.31     467    3205     481 3206.41   494.9 3211.68
   513.6 3213.11   526.3    3220   564.4 3227.92   610.9  3243.4   687.1 3261.04
   759.1 3284.88   805.6  3303.5   822.5 3313.12   839.5 3320.17   860.6 3331.41
   890.2 3350.39   910.1  3358.6   932.6 3372.23   945.3 3375.96     958 3382.97
#Mann= 4 ,-1,0
       0     .06       0      50      .1       0   454.3    .045       0
     481      .1       0
Bank Sta=454.3,481
XS Rating Curve= 0 ,0
Exp/Cntr=0.3,0.1

Type RM Length L Ch R = 1 ,5522    ,282.9,293.7,296.3
XS GIS Cut Line= 3
2187796.05840818482999.8924897832188235.62830847 483007.15810797
2188829.59259522482789.189562373
#Sta/Elev= 30
       0 3385.74    24.1 3383.06    40.1 3375.06    80.1  3362.4    99.8 3350.97
   108.1  3343.1   123.4 3335.92   164.1  3309.2   224.1 3282.04   248.2 3279.57
   299.8 3267.81     332 3265.49   440.2 3247.32     453 3242.07   461.5  3235.5
   491.3 3219.66   513.3 3217.68   535.1  3198.8   549.83195.515   563.8 3194.74
   577.43195.734   603.7 3200.18     638 3199.26     666 3205.74   729.9 3239.42
   851.8 3273.45   887.6  3286.2   989.9 3328.13  1037.5 3354.17  1072.3 3380.46
#Mann= 4 ,-1,0
       0     .06       0      50      .1       0   549.8    .045       0
   577.4      .1       0
Bank Sta=549.8,577.4
XS Rating Curve= 0 ,0
Exp/Cntr(USF)=0,0
Exp/Cntr=0.3,0.1

Type RM Length L Ch R = 1 ,5228    ,434.5,434.9,442.2
XS GIS Cut Line= 3
2187908.54921475483281.4220881082188274.94741592483199.105946457
2188978.99782192483153.498643839
#Sta/Elev= 30
       0 3362.94    24.2  3360.5    61.1 3335.11      97 3328.75   147.2 3301.64
   184.1 3302.81   233.3 3297.41   264.4 3283.87   307.1 3259.82   404.9 3234.09
   440.9  3213.5   464.9 3204.82     489 3200.77   521.1 3189.13   585.2  3188.6
   597.2 3182.56   617.3 3181.09   625.3 3182.25   633.3 3186.28   665.4 3188.27
   713.5 3222.24   737.5 3225.85   773.6 3239.81   805.7 3246.78   849.8 3265.77
   881.8 3270.49     978 3307.41   994.1 3310.33  1050.2 3341.59  1081.1 3366.21
#Mann= 5 ,-1,0
       0      .1       0      10     .06       0     140      .1       0
   597.2    .045       0   625.3      .1       0
Bank Sta=597.2,625.3
XS Rating Curve= 0 ,0
Exp/Cntr=0.3,0.1

Type RM Length L Ch R = 1 ,4793    ,222.9,221.3,218.5
XS GIS Cut Line= 3
2188036.33019302483622.1282017452188368.71954493483570.028193979
  2189048.652577 483585.43778953
#Sta/Elev= 30
       0 3334.18    44.4 3333.67   101.1 3306.78   137.5 3300.56   157.7 3288.62
   198.2 3271.05   219.5 3257.02   238.7 3248.43   327.8 3221.16   351.9 3211.91
   443.9 3190.19   483.9  3176.1   511.9 3168.64     544 3168.69   585.5 3164.73
     596 3162.98   624.6 3164.18     636 3169.52     672 3167.46     684 3170.58
     704 3172.33     740 3186.42     760 3198.32     776  3210.7     824 3237.27
     888 3250.62     908 3260.46   948.1 3273.73   972.1 3285.96  1016.6 3299.58
#Mann= 4 ,-1,0
       0     .06       0     110      .1       0   585.5    .045       0
   624.6      .1       0
Bank Sta=585.5,624.6
XS Rating Curve= 0 ,0
Exp/Cntr=0.3,0.1

Type RM Length L Ch R = 1 ,4572    ,254.9,251.5,241
XS GIS Cut Line= 4
2188149.49809238483819.8115770142188454.05464272483774.201658848
2188826.29042646483758.0174943382189011.67267449 483706.52242544
#Sta/Elev= 30
       0 3318.34    15.2 3317.18    22.3 3314.84    43.4 3302.81   132.1 3246.15
   160.4 3232.23   204.9 3214.35   229.2  3206.3   285.8 3191.58   306.1  3188.7
   330.2  3175.1   338.1 3167.18   350.1 3158.87   358.1 3154.63   370.1  3152.2
   382.1 3151.13   410.7 3152.83   490.2 3161.71   538.3 3175.96   562.3 3187.44
   582.3 3194.97   610.4 3200.69   658.4 3215.06   690.8 3222.71   719.9 3224.61
     778 3244.18   815.3 3248.14   833.1 3247.19   852.7 3251.39   872.9 3259.46
#Mann= 4 ,-1,0
       0     .06       0      90      .1       0   370.1    .045       0
   410.7      .1       0
Bank Sta=370.1,410.7
XS Rating Curve= 0 ,0
Exp/Cntr(USF)=0,0
Exp/Cntr=0.3,0.1

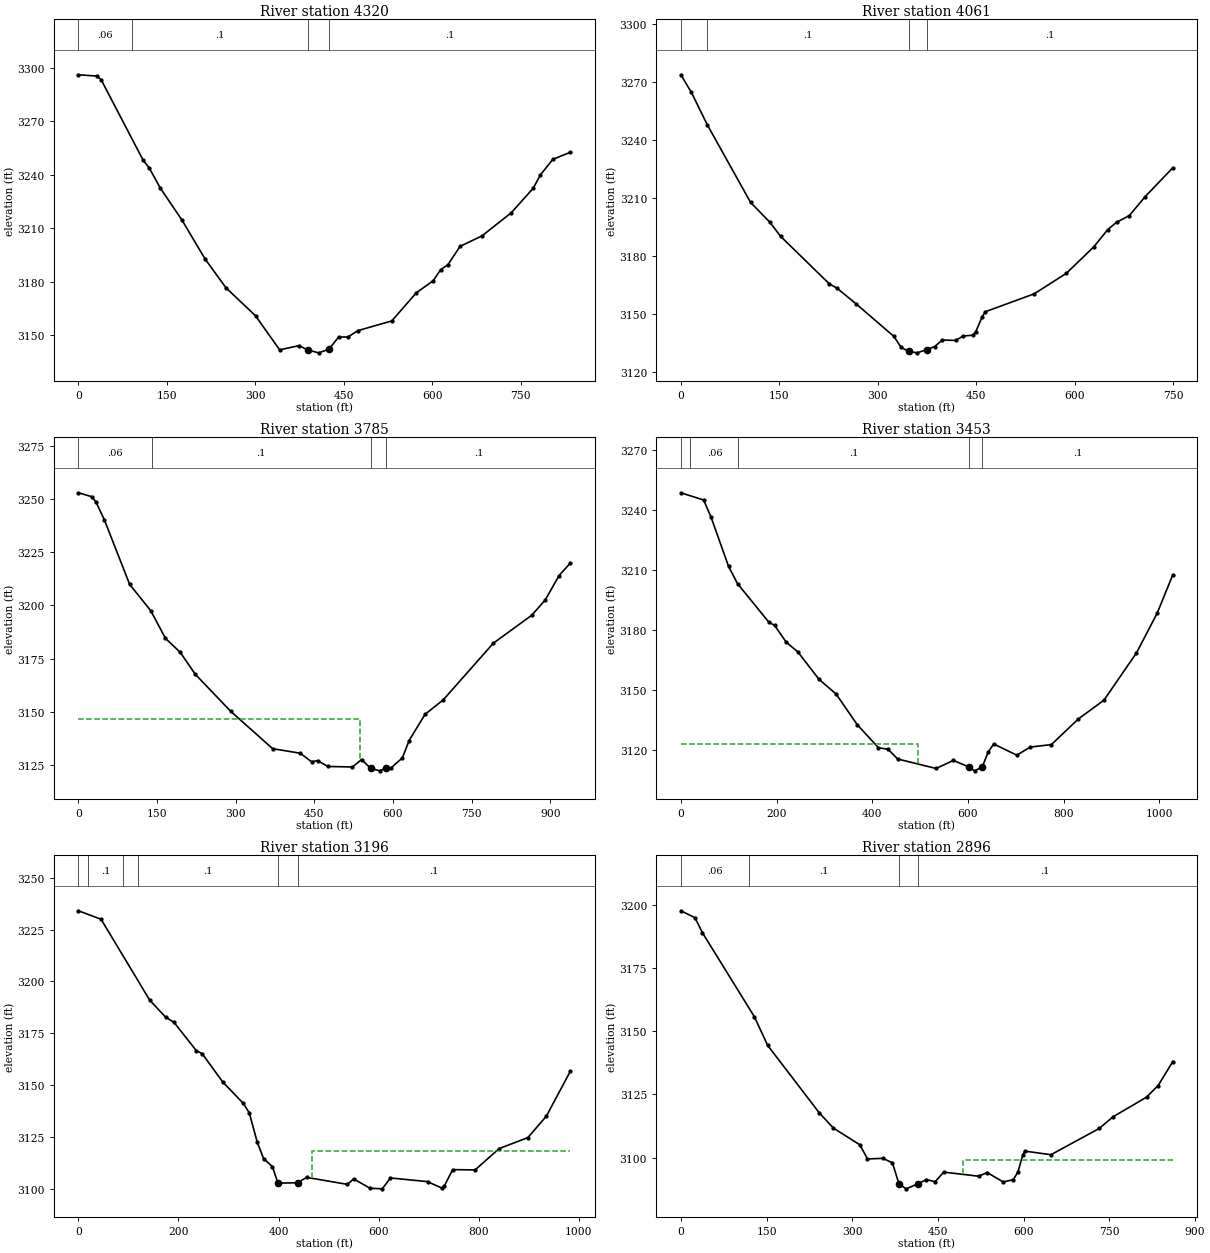
Type RM Length L Ch R = 1 ,4320    ,266.3,259.5,248.1
XS GIS Cut Line= 2
2188254.03291918484093.9483134462189061.03824396483882.052232628
#Sta/Elev= 30
       0 3296.16    31.2 3295.43    38.4 3293.45   109.7 3248.25   120.3 3243.79
   138.7 3232.68     176 3214.41     215 3192.71   250.3 3176.62   300.5 3160.89
   341.3 3141.81   374.4  3144.2   388.9 3141.73   407.5 3140.14   424.9 3142.16
   441.3 3149.03   457.1 3149.01   473.7 3152.57   531.6 3158.06   572.9 3173.77
   601.9 3180.61   614.3 3186.79   626.7 3189.56   647.4 3199.89   684.6 3205.78
   734.2 3218.73   771.4 3232.47   783.8 3240.05   804.5 3248.65   834.4 3252.69
#Mann= 4 ,-1,0
       0     .06       0      90      .1       0   388.9    .045       0
   424.9      .1       0
Bank Sta=388.9,424.9
XS Rating Curve= 0 ,0
Exp/Cntr=0.3,0.1

Type RM Length L Ch R = 1 ,4061    ,288.9,276.4,258.8
XS GIS Cut Line= 4
2188400.53887982484341.8278554262188660.95679967484278.562485066
2188922.84600721484104.9505384982189064.08962476484015.201989849
#Sta/Elev= 30
       0 3273.85    16.1 3264.68      40 3248.11   106.2 3207.77   135.5 3197.57
   151.9 3190.24     226 3165.67   237.9 3163.37   267.2  3155.2   324.6 3138.41
   335.7 3132.68   347.13130.732   359.9 3129.91   375.2 3131.62   386.8 3133.18
   398.3 3136.56   418.5 3136.33   430.2 3138.63   444.5 3139.02   449.4 3140.93
     459 3148.49   463.8 3151.18   538.4 3160.46   587.3 3171.07   629.4 3184.84
   650.1 3193.59   663.8 3197.48   683.3 3200.95   707.6 3210.83   749.5 3225.68
#Mann= 4 ,-1,0
       0     .06       0      40      .1       0   347.1    .045       0
   375.2      .1       0
Bank Sta=347.1,375.2
XS Rating Curve= 0 ,0
Exp/Cntr(USF)=0,0
Exp/Cntr=0.3,0.1

Type RM Length L Ch R = 1 ,3785    ,303.3,331.7,359.5
XS GIS Cut Line= 3
2188499.12303902484617.8033470242188867.44183408484577.837533136
2189084.13234702484053.035739732
#Sta/Elev= 30
       0 3253.06    25.2 3251.24    33.2 3248.82    49.3 3240.42    97.6 3209.94
   137.9 3197.54     166 3184.51   194.2 3177.93   222.9 3167.58   290.7  3150.1
   370.5 3132.55   423.1 3130.42   444.8 3126.38   456.2 3126.95   475.7 3124.18
   522.7 3123.94   540.1 3127.43   557.3 3123.34   574.6 3122.12   587.6 3123.53
   596.2 3123.49   617.9  3128.2   630.8 3136.39   661.1 3148.71   695.8 3155.53
   791.6 3182.26   864.7 3195.38   890.5 3202.59   916.7 3214.04   938.3 3219.96
#Mann= 4 ,-1,0
       0     .06       0     140      .1       0   557.3    .045       0
   587.6      .1       0
#XS Ineff= 2 , 0
          536.14 3146.38
Permanent Ineff=
       F       F
Bank Sta=557.3,587.6
XS Rating Curve= 0 ,0
Exp/Cntr=0.3,0.1

Type RM Length L Ch R = 1 ,3453    ,263.5,257,254.9
XS GIS Cut Line= 3
2188512.95548447484678.3197129082189298.62310708484609.169191817
2189453.10831377484426.729519153
#Sta/Elev= 30
       0 3248.67    47.4 3245.06    63.1 3236.46    99.6 3211.88   118.4 3203.21
   183.9 3183.96     196 3182.33   220.1 3173.96   244.2 3169.19   288.3  3155.5
   324.5 3148.01   368.6 3132.71   412.8 3121.23   432.9 3120.45     453 3115.59
   533.3 3110.85   569.4 3114.87   601.5 3111.64   613.6 3109.67   629.6 3111.52
   641.7 3118.85   653.7 3123.11   701.9  3117.5     730 3121.55   774.2  3122.8
   830.6 3135.63     884 3144.98     952 3168.64   995.4 3188.58  1027.8 3207.63
#Mann= 5 ,-1,0
       0      .1       0      20     .06       0     120      .1       0
   601.5    .045       0   629.6      .1       0
#XS Ineff= 2 , 0
          496.49 3123.12
Permanent Ineff=
       F       F
Bank Sta=601.5,629.6
XS Rating Curve= 0 ,0
Exp/Cntr(USF)=0,0
Exp/Cntr=0.3,0.1

Type RM Length L Ch R = 1 ,3196    ,315.9,299.6,289.2
XS GIS Cut Line= 4
2188619.49455749484842.8320477412188882.93882592484883.880120183
2189334.62029517484787.2198459952189498.91854877484592.410952259
#Sta/Elev= 30
       0 3234.07    45.2 3229.97   142.4 3190.98   174.3 3182.71     191 3180.24
   235.5 3166.63   247.6 3165.04   288.3  3151.5   329.2 3141.21   341.5  3136.6
   357.5 3122.34   370.2 3114.46   387.9 3110.56   398.8 3102.65   438.4 3102.82
   456.1 3105.42   537.9 3102.03   550.1 3104.69   582.9 3100.17   607.4 3099.88
   623.8 3105.13   697.9 3103.36     726 3100.31   731.1  3101.1   748.1 3109.14
     793 3109.02   841.1  3119.3   898.5 3124.61   935.5 3134.96   983.4 3156.61
#Mann= 6 ,-1,0
       0     .06       0      20      .1       0      90     .06       0
     120      .1       0   398.8    .045       0   438.4      .1       0
#XS Ineff= 2 , 0
                          467.74         3118.08
Permanent Ineff=
       F       F
Bank Sta=398.8,438.4
XS Rating Curve= 0 ,0
Exp/Cntr=0.3,0.1

Type RM Length L Ch R = 1 ,2896    ,254.1,249.4,245
XS GIS Cut Line= 3
2188927.94761484 485214.823858232189186.15860317485061.221424148
2189628.42768061484716.940106378
#Sta/Elev= 30
       0  3197.6    24.7 3194.86    37.5    3189   128.4 3155.82   151.9 3144.41
   242.3 3117.73   266.9 3111.74   313.3 3105.11   326.6 3099.53   353.7 3099.77
   370.3 3097.97   381.7 3089.68   394.2 3087.72   414.5 3089.68   429.7  3091.4
   444.9 3090.52   460.1 3094.33     521 3092.71   536.2 3094.15   564.1 3090.44
   581.8 3091.34   589.8 3094.33   598.3 3101.05   602.1 3102.63   647.7  3101.2
   732.3  3111.6   756.3 3116.18     815 3123.94   835.3 3128.54   860.9    3138
#Mann= 4 ,-1,0
       0     .06       0     120      .1       0   381.7    .045       0
   414.5      .1       0
#XS Ineff= 2 , 0
                          494.45         3099.24
Permanent Ineff=
       F       F
Bank Sta=381.7,414.5
XS Rating Curve= 0 ,0
Exp/Cntr(USF)=0,0
Exp/Cntr=0.3,0.1

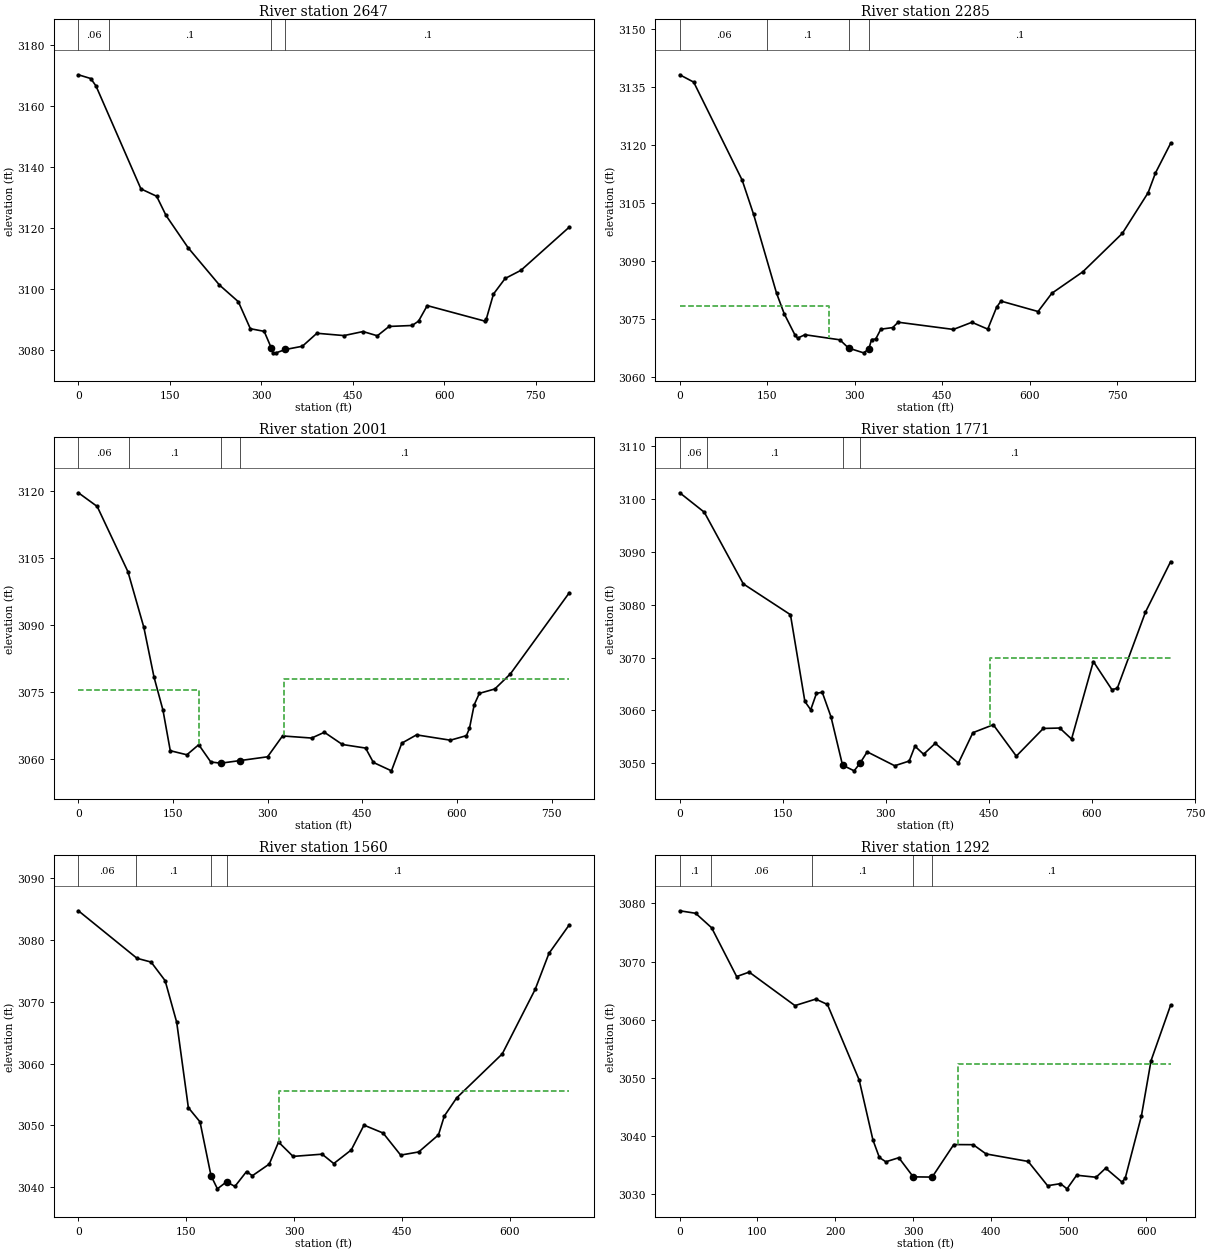
Type RM Length L Ch R = 1 ,2647    ,367.9,361.5,357.8
XS GIS Cut Line= 2
2189195.32946868485460.795008725     2189702.501      484835.873
#Sta/Elev= 30
       0 3170.27    20.2 3169.04    28.8 3166.62   102.5 3132.86   128.3 3130.44
   143.7 3124.14   179.8 3113.58   231.3 3101.32   262.2 3095.87   281.9 3087.01
   304.6 3086.15     316  3080.8   318.9 3079.15   324.1  3079.1   339.5  3080.2
   367.2 3081.26     391 3085.52   435.4 3084.76   466.7 3086.08   490.1 3084.69
   509.3 3087.75   547.2 3088.07   557.7 3089.51   571.9 3094.59   665.8 3089.53
   668.6 3090.08   680.5 3098.38   699.6 3103.48   725.5 3106.15   804.8 3120.33
#Mann= 4 ,-1,0
       0     .06       0      50      .1       0     316    .045       0
   339.5      .1       0
Bank Sta=316,339.5
XS Rating Curve= 0 ,0
Exp/Cntr=0.3,0.1

Type RM Length L Ch R = 1 ,2285    ,277.9,284.6,283.2
XS GIS Cut Line= 2
 2189549.0151096485691.7685491812189942.18622084484948.134466993
#Sta/Elev= 30
       0 3138.19    23.9 3136.29     107 3110.89   126.6 3102.02   165.8 3081.67
   178.9 3076.35   197.5 3070.79     202 3069.99   214.4 3070.88   274.4 3069.56
   289.2 3067.43     315 3066.19   323.9 3067.17   328.7 3069.64   335.8 3069.76
   344.6 3072.31   364.9 3072.73   374.2 3074.12   468.9 3072.25   500.6  3074.1
   527.8 3072.33   542.9 3077.97   550.4 3079.59     614 3076.89   637.6 3081.61
   690.7 3087.17   758.5 3097.14   802.6 3107.65   815.2 3112.77   841.2 3120.44
#Mann= 4 ,-1,0
       0     .06       0     150      .1       0   289.2    .045       0
   323.9      .1       0
#XS Ineff= 2 , 0
          255.84 3078.26
Permanent Ineff=
       F       F
Bank Sta=289.2,323.9
XS Rating Curve= 0 ,0
Exp/Cntr=0.3,0.1

Type RM Length L Ch R = 1 ,2001    ,234.7,230,221.7
XS GIS Cut Line= 3
2189774.13455109485802.316908429 2190014.5479538485423.526023923
2190085.83332321485102.042985413
#Sta/Elev= 30
       0 3119.57    29.8 3116.51    78.5 3101.92   103.7 3089.49   119.8 3078.38
     134 3070.98   145.6 3061.91   171.9    3061   190.7 3063.25   209.8 3059.39
   225.5 3059.12   256.4 3059.71   299.8 3060.55   323.5 3065.21   369.6 3064.74
   389.8 3066.03   418.3  3063.3   455.1  3062.5   467.4 3059.29   496.1 3057.41
   512.5  3063.6   535.8 3065.45   589.5 3064.26   614.9 3065.28   619.7  3066.9
   627.2 3072.17   635.4 3074.73   659.9 3075.71   684.6 3079.09   777.9 3097.22
#Mann= 4 ,-1,0
       0     .06       0      80      .1       0   225.5    .045       0
   256.4      .1       0
#XS Ineff= 2 , 0
          191.14 3075.39   325.9         3077.94
Permanent Ineff=
       F       F
Bank Sta=225.5,256.4
XS Rating Curve= 0 ,0
Exp/Cntr(USF)=0,0
Exp/Cntr=0.3,0.1

Type RM Length L Ch R = 1 ,1771    ,214.1,210.3,206.7
XS GIS Cut Line= 3
2190009.63084558485872.4318580132190085.36683686485766.358792041
2190269.17698506485211.985860523
#Sta/Elev= 30
       0 3101.14    35.7 3097.47    92.5 3083.92   161.1  3078.1   182.1  3061.7
   190.6 3060.13     199 3063.25   207.4 3063.43   220.1  3058.8   236.9 3049.67
   253.8 3048.59   262.2    3050   272.8 3052.18   312.8 3049.55   333.9 3050.44
   342.3 3053.25   354.9 3051.72   371.8 3053.79   405.5 3050.04   426.6  3055.8
   456.3  3057.3   489.8 3051.37   529.1  3056.6     553 3056.68   570.2  3054.6
   601.9 3069.25   628.8 3063.96   636.7 3064.17   677.8  3078.6   714.4 3088.13
#Mann= 4 ,-1,0
       0     .06       0      40      .1       0   236.9    .045       0
   262.2      .1       0
#XS Ineff= 2 , 0
                          451.41          3069.9
Permanent Ineff=
       F       F
Bank Sta=236.9,262.2
XS Rating Curve= 0 ,0
Exp/Cntr=0.3,0.1

Type RM Length L Ch R = 1 ,1560    ,265.2,268.3,271.2
XS GIS Cut Line= 3
2190230.47698582485903.9047745342190299.62750691485805.328499788
2190382.01961714485249.181755698
#Sta/Elev= 30
       0 3084.73    81.5 3077.04   101.1 3076.43   120.6 3073.42   136.7 3066.68
   152.9 3052.87   169.1 3050.57   184.4 3041.86   193.3 3039.73     206 3040.87
   217.6 3040.12   233.8 3042.53   241.9 3041.85   265.4 3043.74   278.3  3047.3
   298.5 3044.98   338.9 3045.34   355.1 3043.82   379.4 3046.02   397.1 3050.04
   423.7 3048.76   448.1 3045.19   473.2  3045.7   500.7 3048.46   508.8 3051.51
     526 3054.45   589.4 3061.57   635.2 3072.02   654.3 3077.83   682.6 3082.46
#Mann= 4 ,-1,0
       0     .06       0      80      .1       0   184.4    .045       0
     206      .1       0
#XS Ineff= 2 , 0
                          279.02         3055.63
Permanent Ineff=
       F       F
Bank Sta=184.4,206
XS Rating Curve= 0 ,0
Exp/Cntr(USF)=0,0
Exp/Cntr=0.3,0.1

Type RM Length L Ch R = 1 ,1292    ,117.3,141.9,167.2
XS GIS Cut Line= 3
2190394.60058897485963.8058688822190556.40159521485782.299786682
2190663.45242768485408.973802292
#Sta/Elev= 30
       0 3078.72    20.4 3078.29      41  3075.8    73.2 3067.41    89.3 3068.18
   148.2 3062.42     175 3063.54     190 3062.61   230.8 3049.64   248.5 3039.33
   256.8 3036.31   265.1 3035.57   281.8 3036.27   300.4 3032.98   324.7 3032.94
   352.5 3038.53   377.5 3038.51   394.1 3036.92   448.2 3035.63   473.2 3031.46
   489.8 3031.81   498.2 3030.92   510.6 3033.26   535.6 3032.91   547.9 3034.47
   568.9 3032.08   573.1 3032.76   593.9 3043.45   606.3 3052.96   631.5  3062.5
#Mann= 5 ,-1,0
       0      .1       0      40     .06       0     170      .1       0
   300.4    .045       0   324.7      .1       0
#XS Ineff= 2 , 0
                          358.45         3052.33
Permanent Ineff=
       F       F
Bank Sta=300.4,324.7
XS Rating Curve= 0 ,0
Exp/Cntr=0.5,0.3