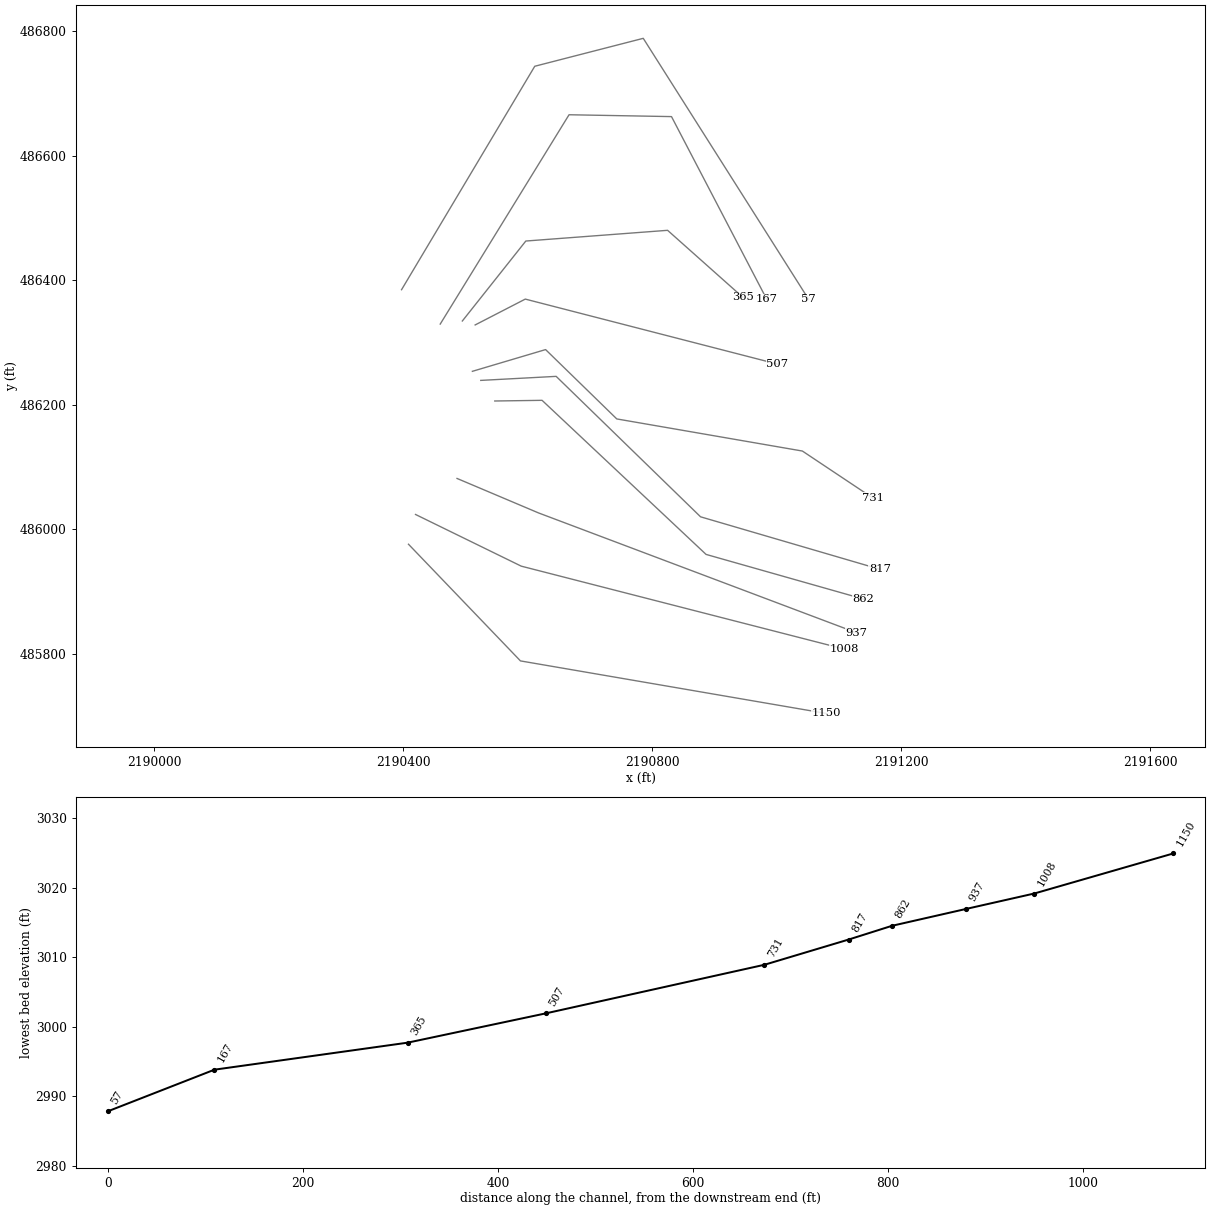
HEC-RAS study SUGARCK.prj: SUGARCK

--- SUGARCK.g01 (geometry) --- (continued)

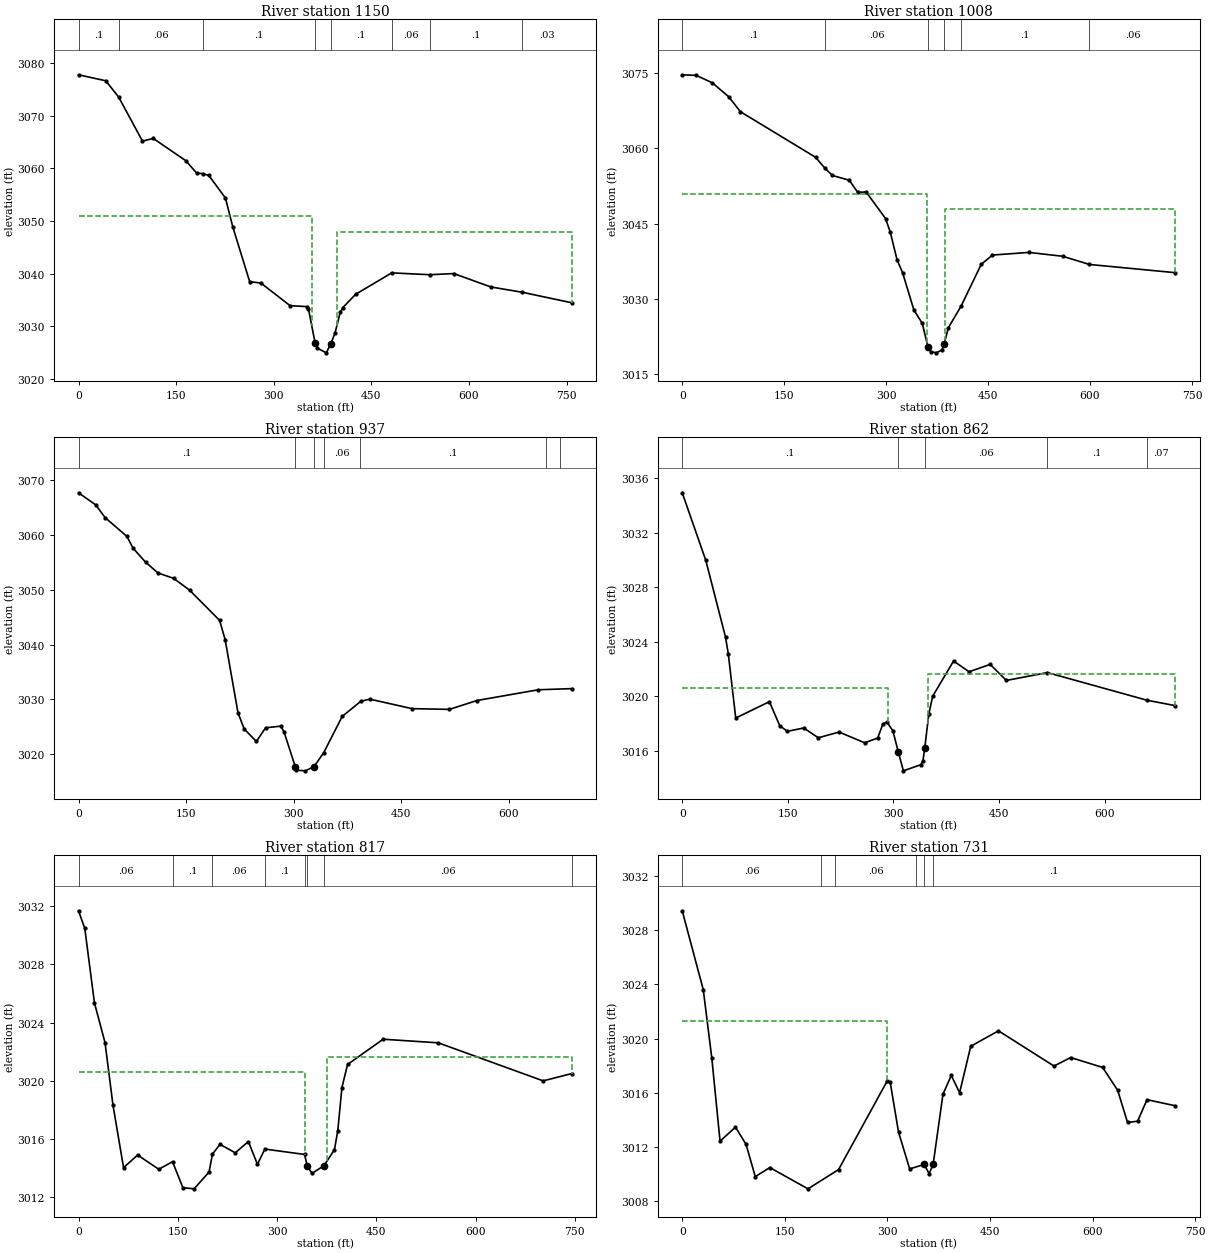
Type RM Length L Ch R = 1 ,1150    ,145.6,142.7,140.5
XS GIS Cut Line= 3
2190408.04194756485976.0859628212190587.93267389485788.647373847
2191078.54374571485704.362907664
#Sta/Elev= 30
       0 3077.81    41.8 3076.67    61.6 3073.59    98.3 3065.19   114.9  3065.7
   164.8 3061.47   181.4 3059.13   190.8    3059   200.2 3058.67   225.8 3054.36
     237  3048.9     263 3038.47   280.3 3038.19     325  3033.9   351.2 3033.71
   353.4 3033.26   363.5 3026.81   366.9 3025.82   380.8 3024.92   387.7 3026.67
     394 3028.62   402.1  3032.6   406.2 3033.53   425.8 3036.05   481.2 3040.13
   540.1 3039.78   576.6    3040   633.4 3037.46   681.9 3036.44   757.6 3034.45
#Mann= 8 ,-1,0
       0      .1       0    61.6     .06       0   190.8      .1       0
   363.5    .045       0   387.7      .1       0   481.2     .06       0
   540.1      .1       0   681.9     .03       0
#XS Ineff= 2 , 0
       0  358.61    3051  396.79       0    3048
Permanent Ineff=
       F       F
Bank Sta=363.5,387.7
XS Rating Curve= 0 ,0
Exp/Cntr(USF)=0,0
Exp/Cntr=0.5,0.3

Type RM Length L Ch R = 1 ,1008    ,73.8,70.4,68.5
XS GIS Cut Line= 3
2190419.36374153486023.889092895  2190589.190651485940.862603819
2191108.73519628485807.517030455
#Sta/Elev= 30
       0 3074.73    20.6 3074.61    44.5 3073.11    68.4 3070.34    85.5 3067.36
   196.2 3058.24   210.3    3056     221 3054.61   245.8 3053.65   258.2 3051.23
   270.6 3051.31   299.2 3045.99   306.2 3043.22     316  3037.8   324.3 3035.14
   340.8 3027.74   353.2 3025.05   361.4  3020.4   365.6 3019.41   373.8 3019.16
   382.1 3019.73   385.1 3020.83   391.7 3024.21   410.3  3028.5   439.9 3036.84
   456.4  3038.7   510.1 3039.23   559.7 3038.46   599.2 3036.82   725.4 3035.18
#Mann= 6 ,-1,0
       0      .1       0   210.3     .06       0   361.4    .045       0
   385.1     .06       0   410.3      .1       0   599.2     .06       0
#XS Ineff= 2 , 0
       0  360.55    3051  385.97       0    3048
Permanent Ineff=
       F       F
Bank Sta=361.4,385.1
XS Rating Curve= 0 ,0
Exp/Cntr(USF)=0,0
Exp/Cntr=0.5,0.3

Type RM Length L Ch R = 1 ,937     ,87,75.6,64.3
XS GIS Cut Line= 3
2190486.03652821486081.7560398272190616.86614736486026.405047109
2191127.60485289485833.934549706
#Sta/Elev= 30
       0 3067.73      24 3065.52    37.1  3063.2    67.5 3059.76    76.2  3057.6
    93.5 3055.06   110.9 3053.08   132.6  3052.1   154.9 3049.95   196.9 3044.41
   204.6 3040.89   222.5 3027.55   231.1 3024.58   248.2  3022.3     261 3024.79
   282.2  3025.1   286.7 3024.07   302.5 3017.66   303.9 3017.05   316.6 3016.93
   328.7 3017.72   342.2 3020.27   367.9 3026.87   393.9 3029.64   406.4 3030.03
   465.4 3028.29   517.5 3028.16     556 3029.78   641.4 3031.74   687.9 3031.95
#Mann= 7 ,-1,0
       0      .1       0   302.5    .045       0   328.7      .1       0
  342.06     .06       0  392.06      .1       0  652.06     .07       0
  672.06     .06       0
Bank Sta=302.5,328.7
XS Rating Curve= 0 ,0
Exp/Cntr(USF)=0,0
Exp/Cntr=0.5,0.3

Type RM Length L Ch R = 1 ,862     ,43.2,44.6,47.4
XS GIS Cut Line= 4
2190546.67102477486206.1699757292190622.64010991486207.245761718
 2190886.0732483485959.7322604272191138.92664685485888.027565316
#Sta/Elev= 30
       0 3034.95    33.5 3029.98    61.5 3024.34    65.5 3023.09      76  3018.4
   123.8  3019.6   138.5 3017.84   149.4 3017.42   172.5 3017.67   193.3 3016.95
   222.8 3017.37   259.2 3016.58   277.6 3016.93   285.1 3017.97   290.8  3018.1
   299.2 3017.46   306.8 3015.93   314.1 3014.52   338.9 3014.97   341.9 3015.25
   344.5  3016.2   350.2 3018.69   355.8 3020.01   385.4 3022.59   407.4  3021.8
   437.4 3022.34   460.4 3021.16   518.6 3021.74     660 3019.71   700.3 3019.31
#Mann= 5 ,-1,0
       0      .1       0   306.8    .045       0   344.5     .06       0
   518.6      .1       0     660     .07       0
#XS Ineff= 2 , 0
       0  291.57  3020.6  348.59       0  3021.6
Permanent Ineff=
       F       F
Bank Sta=306.8,344.5
XS Rating Curve= 0 ,0
Exp/Cntr(USF)=0,0
Exp/Cntr=0.5,0.3

Type RM Length L Ch R = 1 ,817     ,72.2,86.3,99.7
XS GIS Cut Line= 4
2190524.15323456486239.2547736492190645.28369784486245.739861199
2190877.26740855486020.115161573 2191165.3441661 485935.83069539
#Sta/Elev= 30
       0  3031.7     9.5 3030.48    24.1 3025.35    40.1 3022.61    52.1  3018.3
    68.1    3014    89.3 3014.87   121.3 3013.89   142.1 3014.41   157.7 3012.62
   174.7 3012.54   197.3  3013.7   202.4 3014.93   213.9 3015.61   236.9 3015.02
   256.7  3015.8   270.4 3014.23   281.6 3015.28   341.6 3014.91   345.9 3014.09
   352.9 3013.61   370.9 3014.13   386.8 3015.24   391.8 3016.54   398.1 3019.52
   406.6 3021.11   460.4 3022.85   543.8  3022.6   702.2 3019.98   745.1 3020.48
#Mann= 8 ,-1,0
       0     .06       0   142.1      .1       0   202.4     .06       0
   281.6      .1       0   341.6     .06       0   345.9    .045       0
   370.9     .06       0   745.1     .07       0
#XS Ineff= 2 , 0
       0  341.76  3020.6  375.31       0  3021.6
Permanent Ineff=
       F       F
Bank Sta=345.9,370.9
XS Rating Curve= 0 ,0
Exp/Cntr(USF)=0,0
Exp/Cntr=0.5,0.3

Type RM Length L Ch R = 1 ,731     ,228.4,223.9,215.3
XS GIS Cut Line= 5
2190510.69287951486253.8473080922190628.30100689486288.762678266
2190742.66385808486177.3622999752191040.80443249486125.785238579
2191154.02237214486050.306612146
#Sta/Elev= 30
       0 3029.44    30.8 3023.61    43.3 3018.55    55.3 3012.44    77.9 3013.47
    93.3 3012.21   106.8 3009.82   128.1 3010.49   183.9 3008.92   228.6 3010.34
   300.1 3016.91   304.2 3016.77   316.3 3013.11   332.6 3010.39   353.8 3010.72
     361 3010.04   366.93010.717   381.3  3015.9   393.5 3017.29   405.6 3016.01
   421.9 3019.44   462.5 3020.58   543.7 3017.98     568 3018.61   614.8 3017.88
   636.8 3016.19   651.2 3013.82   665.9 3013.91   679.7  3015.5     721 3015.05
#Mann= 6 ,-1,0
       0     .06       0  202.68      .1       0  222.68     .06       0
  342.33      .1       0   353.8    .045       0   366.9      .1       0
#XS Ineff= 2 , 0
           298.8 3021.27
Permanent Ineff=
       F       F
Bank Sta=353.8,366.9
XS Rating Curve= 0 ,0
Exp/Cntr(USF)=0,0
Exp/Cntr=0.3,0.1

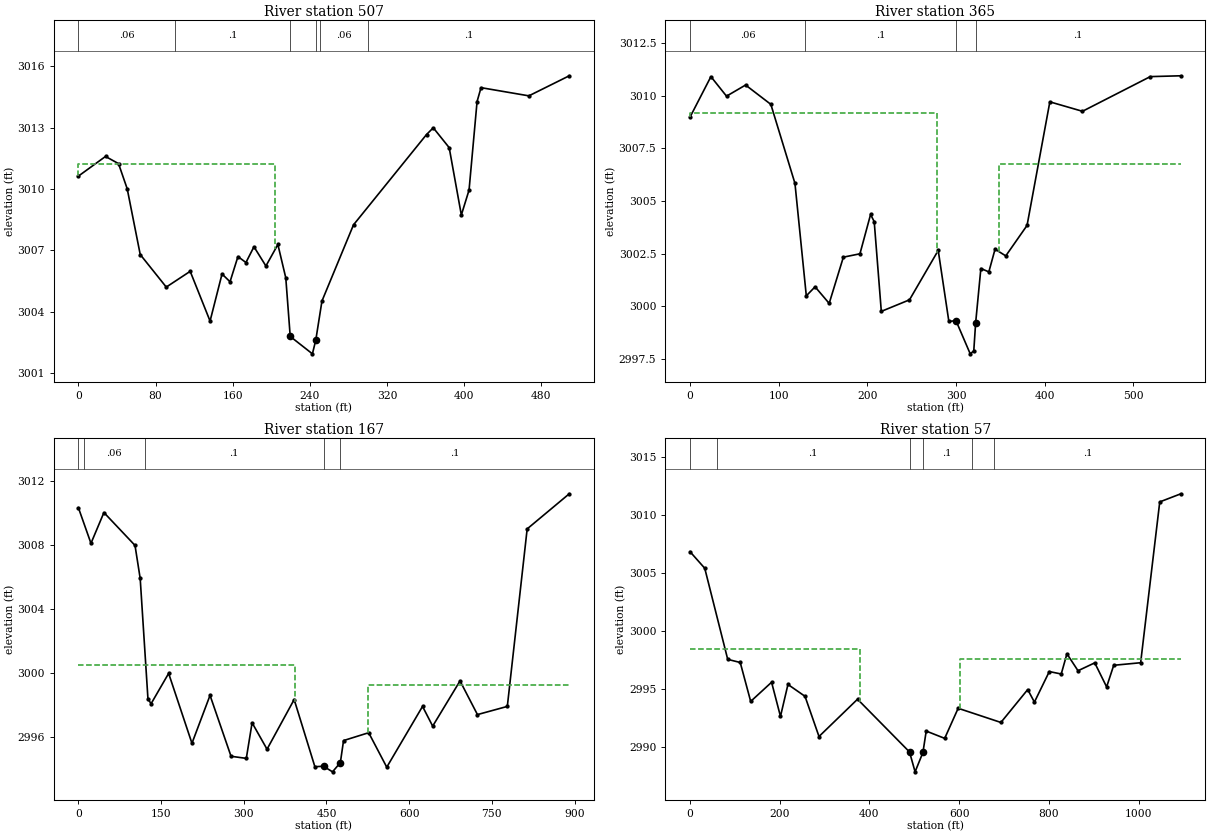
Type RM Length L Ch R = 1 ,507     ,134.5,142.1,149.8
XS GIS Cut Line= 3
2190515.17087879486328.3570747012190595.68141365486369.870319239
2191000.75004218486265.458219341
#Sta/Elev= 30
       0 3010.63    28.1 3011.59    41.6 3011.24    50.6 3010.01    64.1  3006.8
    91.1 3005.21   115.9 3005.98   136.5 3003.55   148.9 3005.85   157.2 3005.47
   165.4  3006.7   173.7 3006.41     182 3007.18   194.4 3006.24   206.8 3007.29
     215 3005.66   219.6  3002.8   242.6 3001.95   246.1 3002.62   252.5 3004.53
   285.2 3008.25   360.9 3012.66   367.9 3012.99   384.4 3012.02     397 3008.73
     405 3009.95   413.3 3014.27   417.4 3014.95     467 3014.55   508.9 3015.53
#Mann= 6 ,-1,0
       0     .06       0  100.58      .1       0   219.6    .045       0
   246.1      .1       0  250.58     .06       0  300.58      .1       0
#XS Ineff= 2 , 0
          204.06 3011.22
Permanent Ineff=
       F       F
Bank Sta=219.6,246.1
XS Rating Curve= 0 ,0
Exp/Cntr(USF)=0,0
Exp/Cntr=0.3,0.1

Type RM Length L Ch R = 1 ,365     ,199.6,198.1,195
XS GIS Cut Line= 4
2190494.57312488486334.6978080512190596.53336129486463.141222758
2190824.28869459486480.3552886462190944.78715581486373.098416572
#Sta/Elev= 30
       0 3008.99    23.6 3010.92    41.2 3009.99    62.7 3010.52    91.2  3009.6
   118.4 3005.84   131.2 3000.49   141.1 3000.92     157 3000.13     173 3002.33
   191.7 3002.49   203.7 3004.36   207.8 3004.02   215.8 2999.75   247.6  3000.3
     280 3002.65     292 2999.27     300 2999.31   316.1 2997.73   320.1 2997.87
   322.2  2999.2   328.1 3001.79   337.1 3001.63   344.1 3002.71   356.2 3002.39
   380.2 3003.84   405.9 3009.72   442.7 3009.27   519.2 3010.92   553.7 3010.96
#Mann= 4 ,-1,0
       0     .06       0     130      .1       0     300    .045       0
   322.2      .1       0
#XS Ineff= 2 , 0
          278.26 3009.17   348.8         3006.77
Permanent Ineff=
       F       F
Bank Sta=300,322.2
XS Rating Curve= 0 ,0
Exp/Cntr(USF)=0,0
Exp/Cntr=0.3,0.1

Type RM Length L Ch R = 1 ,167     ,101.7,109.2,115.1
XS GIS Cut Line= 4
2190459.03893941  486329.74121192190665.98292072486666.003617749
2190830.56247809486663.0249729972190983.62747246486369.430475913
#Sta/Elev= 30
       0 3010.32    22.8  3008.1    46.3 3010.02   102.7 3007.97   112.1 3005.91
   126.2 2998.39   131.9  2998.1   163.7 2999.99     206 2995.63   238.8 2998.62
   276.9 2994.82   304.6 2994.69   315.1 2996.91   342.2 2995.26   391.4 2998.36
     429 2994.17     445  2994.2     445 2994.19     461 2993.85   475.22994.423
     481  2995.8   526.6 2996.29   559.4 2994.14   624.3 2997.93   642.7  2996.7
   692.3 2999.52   723.9 2997.42   778.1 2997.93   814.1    3009   890.5 3011.19
#Mann= 5 ,-1,0
       0      .1       0      10     .06       0     120      .1       0
     445    .045       0   475.2      .1       0
#XS Ineff= 2 , 0
          392.57 3000.49   525.1         2999.29
Permanent Ineff=
       F       F
Bank Sta=445,475.2
XS Rating Curve= 0 ,0
Exp/Cntr(USF)=0,0
Exp/Cntr=0.3,0.1

Type RM Length L Ch R = 1 ,57      ,,,
XS GIS Cut Line= 4
2190396.91661313486384.9610574842190610.89351477 486743.89005378
2190785.18115239486788.7561783172191050.92665926486369.430475913
#Sta/Elev= 30
       0 3006.83    32.9  3005.4    84.1 2997.56     112 2997.29   135.3 2993.94
   181.9 2995.59   201.7 2992.65   218.4  2995.4   256.4 2994.38   287.6 2990.92
   373.5 2994.13   489.4 2989.59   501.8 2987.88   519.3 2989.55   526.6 2991.39
   567.8 2990.76   597.8 2993.35   693.1 2992.13   752.9 2994.96   767.8 2993.88
     801 2996.51   827.6  2996.3   840.3 2998.04     865 2996.58   902.3 2997.26
   928.8 2995.19   944.6 2997.05  1004.6 2997.27  1047.2 3011.11  1094.3 3011.81
#Mann= 6 ,-1,0
       0     .06       0      60      .1       0   489.4    .045       0
   519.3      .1       0  627.84     .06       0  677.84      .1       0
#XS Ineff= 2 , 0
          379.52 2998.42   601.2         2997.59
Permanent Ineff=
       F       F
Bank Sta=489.4,519.3
XS Rating Curve= 0 ,0
Exp/Cntr(USF)=0,0
Exp/Cntr=0.3,0.1
LCMann Table=0

Chan Stop Cuts=-1
Use User Specified Reach Order=0
Composite Channel Slope=5